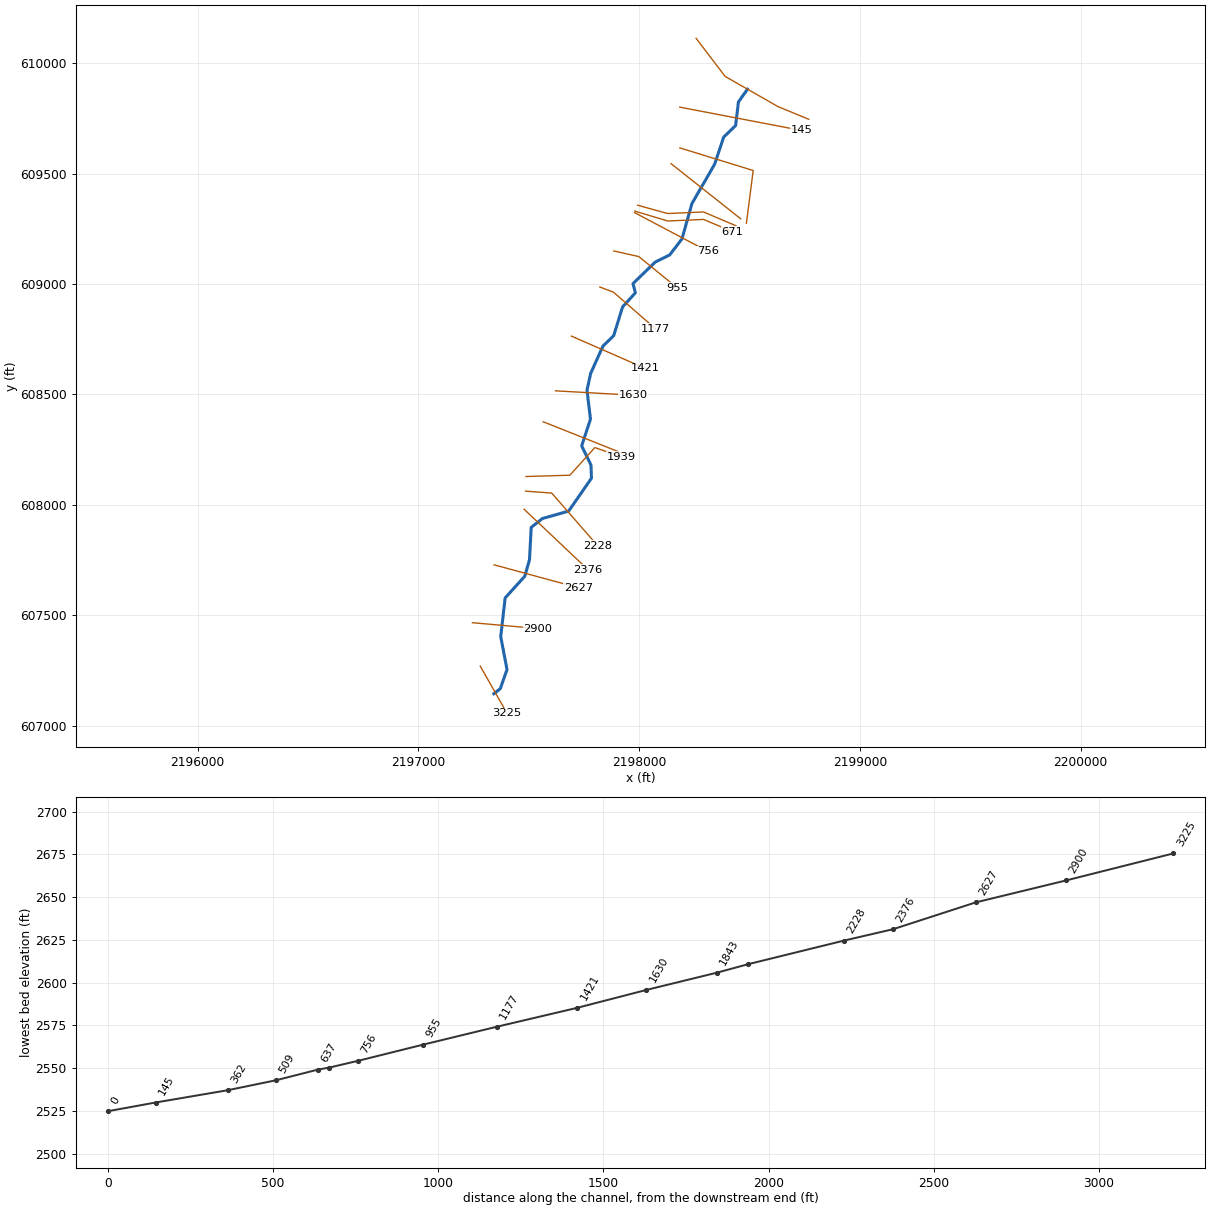
--- ANDRSNCMPR.prj (project) ---

Proj Title=ANDRSNCMPR
Current Plan=p01
Default Exp/Contr=0,0
English Units
Geom File=g01
Flow File=f01
Plan File=p01
Background Map Layer=Inundation Boundary (P100yr Value_0)
BEGIN DESCRIPTION:
----------MODEL BY WOOD PLC 2022----------
AFH study
Randolph County, WV
HEC-RAS Version: RAS 6.2
Vertical Datum: NAVD88
Projection: NAD 1983 StatePlane West Virginia S FIPS 4702 (US Feet)
Terrain: 1-meter LIDAR (FEMA Region III 3DEP collected 2016-2018)
Land Use: 2019 NLCD
Hydrologic Method:
WV SIR2010-5033 regression equations
Additional Model Notes:
Coincident peak with LFRFBUCRV
END DESCRIPTION:
DSS Export Rating Curves= 0
DSS Export Rating Curve Sorted= 0
DSS Export Volume Flow Curves= 0
DXF OffsetX= 0
DXF OffsetY= 0
DXF ScaleX= 0
DXF ScaleY= 0

--- ANDRSNCMPR.p01 (plan) ---

Plan Title=Floodplain
Program Version=6.20
Short Identifier=Floodplain
Geom File=g01
Flow File=f01
Subcritical Flow
K Sum by GR= 0
Std Step Tol= 0.01
Critical Tol= 0.01
Num of Std Step Trials= 20
Max Error Tol= 0.3
Flow Tol Ratio= 0.001
Split Flow NTrial= 30
Split Flow Tol= 0.02
Split Flow Ratio= 0.02
Log Output Level= 0
Friction Slope Method= 1
Unsteady Friction Slope Method= 2
Unsteady Bridges Friction Slope Method= 1
Parabolic Critical Depth
Global Vel Dist= 0 , 0 , 0
Global Log Level= 0
CheckData=True
Encroach Param=-1 ,0,0, 0
Mapping Interval=1HOUR
Computation Time Step Use Courant=        0
Computation Time Step Use Time Series=    0
Computation Time Step Count To Double=0
Computation Time Step Max Doubling=0
Computation Time Step Max Halving=0
Computation Time Step Residence Courant=0
Run HTab= 0
Run UNet= 0
Run Sediment= 0
Run PostProcess= 0
Run WQNet= 0
Run RASMapper=-1
UNET Theta= 0
UNET Theta Warmup= 0
UNET ZTol= 0
UNET ZSATol= 0
UNET MxIter= 0
UNET Max Iter WO Improvement= 0
UNET MaxInSteps= 0
UNET DtIC= 0
UNET DtMin= 0
UNET MaxCRTS= 0
UNET WFStab= 0
UNET SFStab= 0
UNET WFX= 1
UNET SFX= 1
UNET Gravity=32.174
UNET 1D Methodology=Finite Difference
UNET DSS MLevel= 1
UNET Pardiso=0
UNET DZMax Abort= 0
UNET Use Existing IB Tables= 0
UNET Froude Reduction=False
UNET Froude Limit= 0
UNET Froude Power= 0
UNET D1 Cores= 0
UNET WindReference=Eulerian
UNET WindDragFormulation=Hsu (1988)
UNET D2 Coriolis=0
UNET D2 Cores= 0
UNET D2 Theta= 1
UNET D2 Theta Warmup= 1
UNET D2 Z Tol= 0.01
UNET D2 Volume Tol= 0.01
UNET D2 Max Iterations= 20
UNET D2 Equation= 0
UNET D2 RampUpFraction=0.1
UNET D2 TimeSlices= 1
UNET D2 Turbulence Formulation=Non-Conservative (original)
UNET D2 Eddy Viscosity=0.3
UNET D2 Transverse Eddy Viscosity=0.1
UNET D2 Smagorinsky Mixing=0
UNET D2 BCVolumeCheck=0
UNET D2 Cores=0
UNET D2 SolverType=PARDISO (Direct)
UNET D2 Minimum Iterations= 2147483647
UNET D2 Maximum Iterations= 2147483647
UNET D2 Restart Number= 10
UNET D2 Relaxation Coeff=1.3
UNET D2 SOR Precondition Iterations= 10
UNET D2 ILUT Maximum Fill= 8
UNET D2 ILUT Tolerance=1E-08
UNET D1D2 MaxIter= 0
UNET D1D2 ZTol=0.01
UNET D1D2 QTol=0.1
UNET D1D2 MinQTol=1
Write IC File= 0
Write IC File at Fixed DateTime=0
Write IC File at Sim End=0
Echo Input=False
Echo Parameters=False
Echo Output=False
Write Detailed= 0
HDF Write Warmup=0
HDF Write Time Slices=0
HDF Flush=0
HDF Compression= 1
HDF Chunk Size= 1
HDF Spatial Parts= 1
HDF Use Max Rows=0
HDF Fixed Rows= 1
Calibration Method= 0
Calibration Iterations= 20
Calibration Max Change=0.05
Calibration Tolerance=0.2
Calibration Maximum=1.5
Calibration Minimum=0.5
Calibration Optimization Method= 1
WQ AD Non Conservative
WQ ULTIMATE=-1
WQ Max Comp Step=1HOUR
WQ Output Interval=15MIN
WQ Output Selected Increments= 0
WQ Output face flow=0
WQ Output face velocity=0
WQ Output face area=0
WQ Output face dispersion=0
WQ Output cell volume=0
WQ Output cell surface area=0
WQ Output cell continuity=0
WQ Output cumulative cell continuity=0
WQ Output face conc=0
WQ Output face dconc_dx=0
WQ Output face courant=0
WQ Output face peclet=0
WQ Output face adv mass=0
WQ Output face disp mass=0
WQ Output cell mass=0
WQ Output cell source sink temp=0
WQ Output nsm pathways=0
WQ Output nsm derived pathways=0
WQ Create Restart=0
WQ Fixed Restart=0
WQ System Summary=0
WQ Write To DSS=0
Sorting and Armoring Iterations= 10
XS Update Threshold= 0.02
Bed Roughness Predictor= 0
Hydraulics Update Threshold= 0.02
Energy Slope Method= 1
Volume Change Method= 1
Sediment Retention Method= 0
Sediment TS Multiplier= 1
Warm Up Method= 0
XS Weighting Method= 0
Number of US Weighted Cross Sections= 1
Number of DS Weighted Cross Sections= 1
Upstream XS Weight=0
Main XS Weight=1
Downstream XS Weight=0
Number of DS XS's Weighted with US Boundary= 1
Upstream Boundary Weight= 1
Weight of XSs Associated with US Boundary= 0
Number of US XS's Weighted with DS Boundary= 1
Downstream Boundary Weight= 0.5
Weight of XSs Associated with DS Boundary= 0.5
Percentile Method= 0
Sediment Output Level= 3
Mass or Volume Output= 0
Output Increment Type= 1
Profile and TS Output Increment= 1
Transport Output Increment 1
XS Output Flag= 0
XS Output Increment= 10
Read HDF5 Sediment Hotstart= 0
Sediment Hotstart Type= 0
Write Gradation File= 0
Read Gradation Hotstart= 0
Write HDF5 File= 1
Write Binary Output= 1
Write DSS Sediment File= 0
DSS Sediment Output Type= 1
SV Curve= 0
Specific Gage Flag= 0
Subcell Erosion Methods= 0
Subcell Deposition Methods= 0
Advection Scheme= 1
Matrix Solver= 0
Implicit Weighting Factor= 1
Maximum Outer Loop Convergence Iterations= 5
Convergence Maximum Absolute= 0.001
Convergence RMSE= 0.0001
Grain Fractions Max Abs Error= 0.001
Max Subgrid Regions= 1
Max Subgrid Length Scale= 3.402823E+38
Initial Layer Thickness= 3.402823E+38
Min Layer Thickness= 3.402823E+38
Max Layer Thickness= 3.402823E+38
Number of Layers= 5

--- ANDRSNCMPR.f01 (steady flow) ---

Flow Title=Flow
Program Version=6.20
Number of Profiles= 1
Profile Names=P100yr
River Rch & RM=ANDRSNCMPR,Main,3225
     350
Boundary for River Rch & Prof#=ANDRSNCMPR,Main            , 1
Up Type= 0
Dn Type= 1
Dn Known WS=2528.8
DSS Import GetInterval= 0
DSS Import GetPeak= 0
DSS Import FillOption= 0

--- ANDRSNCMPR.g01 (geometry) ---

Geom Title=Geometry
Program Version=6.20

River Reach=ANDRSNCMPR      ,Main
Reach XY= 30
 2197341.6490255607144.0565843142197370.69740686607166.720591247
2197401.35217595607253.6457584352197372.79704855607402.720320567
2197392.84700005607578.1480000022197481.49100003607675.901000008
2197503.01400001 607750.086000012197510.90299998607897.592999995
2197561.59700003607937.870000005     2197680.347607971.203999996
      2197783.91608120.3300000132197781.73600002608180.231999993
     2197739.581608266.8920000052197779.37100005608388.027999997
2197763.68000004 608519.120000022197780.34700002608595.509000018
      2197835.97608719.0010000022197884.43200003608765.822999999
2197924.79200001608896.2040000262197982.84807542 608960.50926517
2197972.09428981 609002.341426762198072.70800003609099.675999999
2198138.68000002609132.3150000132198194.23600003609205.231000006
2198239.07100002      609364.9192198341.91775322609542.788517371
2198382.77799998609665.6480000022198437.09362833609718.223595724
2198449.68800001609825.1370000092198490.95093525609882.873866012

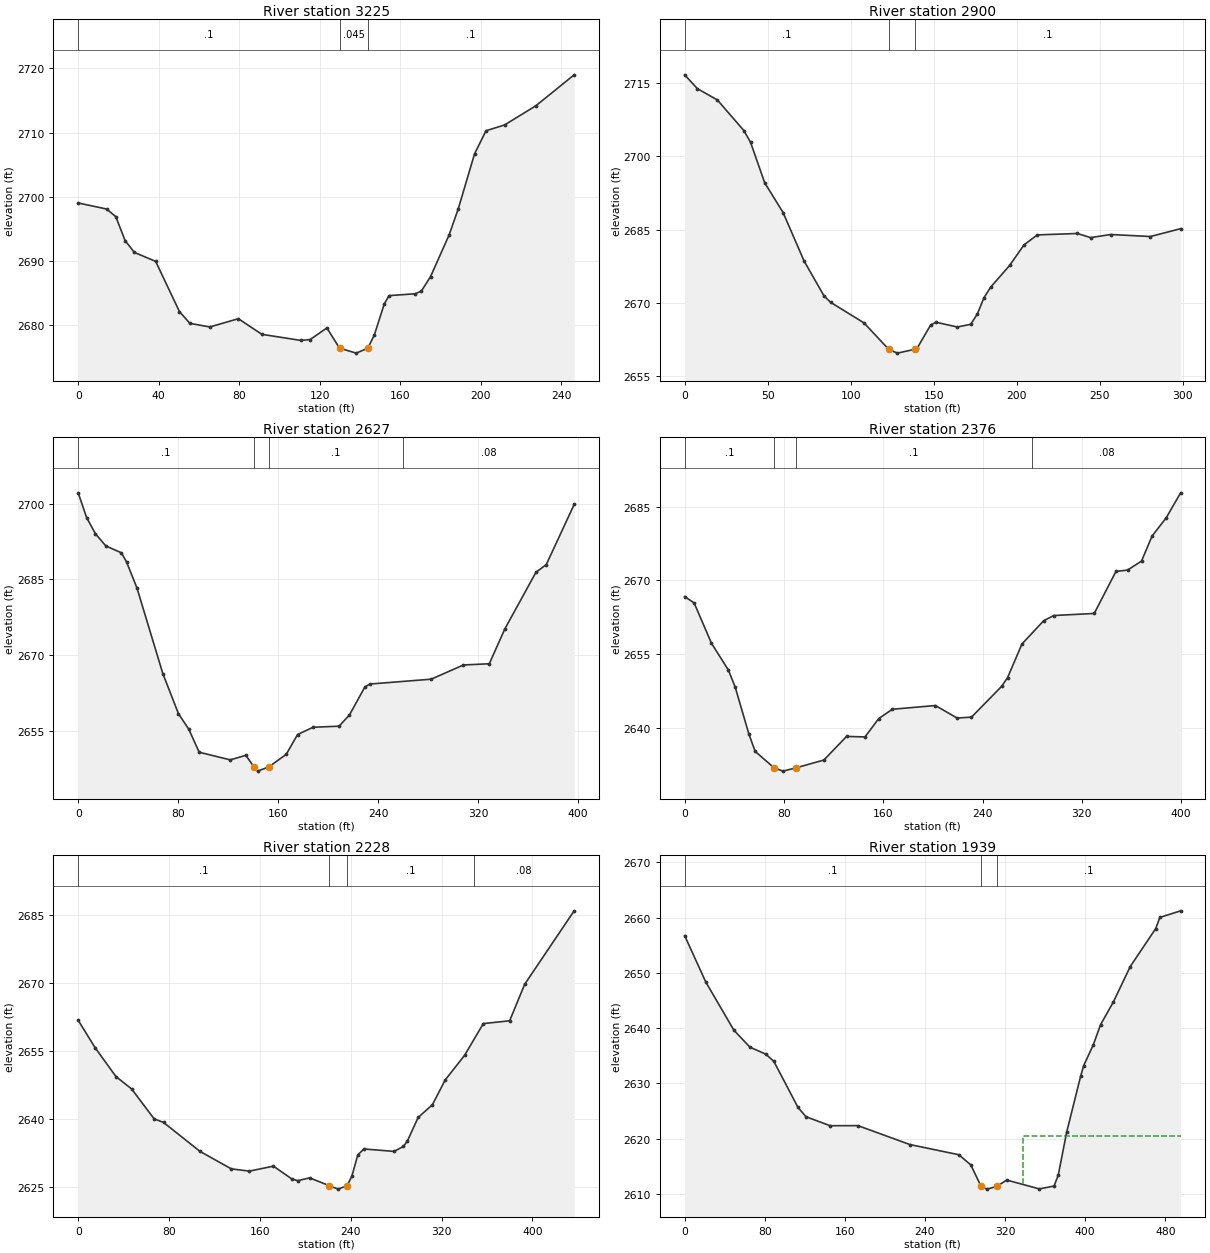
Type RM Length L Ch R = 1 ,3225    ,316.7,325.5,330.2
XS GIS Cut Line= 2
2197279.92032689607269.438664593 2197401.5589425607055.065658861
#Sta/Elev= 30
       0 2699.01    14.1 2698.07    18.7 2696.87    23.3 2693.15    27.9  2691.3
    38.5  2689.9    50.3 2682.08    55.5 2680.23    65.4 2679.67    79.6 2680.96
    91.3 2678.52   110.7 2677.57   115.3 2677.71   123.6 2679.52  129.882676.364
   138.2 2675.59  143.922676.364   147.1 2678.35   152.1 2683.24   154.5 2684.56
   167.6 2684.85   170.6 2685.29   175.1 2687.51   184.3 2693.99   188.9  2698.1
     197 2706.68   202.7 2710.28   211.9 2711.18   227.5 2714.18   246.5    2719
#Mann= 3 ,-1,0
       0      .1       0  129.88    .045       0  143.92      .1       0
Bank Sta=129.88,143.92
XS Rating Curve= 0 ,0
Exp/Cntr(USF)=0,0
Exp/Cntr=0.3,0.1

Type RM Length L Ch R = 1 ,2900    ,274.1,272.6,270.8
XS GIS Cut Line= 2
2197244.59294018607465.880345251 2197542.0655942607439.384805217
#Sta/Elev= 30
       0 2716.62     7.6 2713.81    19.7 2711.48    35.7 2705.21    39.7 2702.81
    48.2 2694.56    59.3 2688.46    71.9 2678.59    83.9 2671.46    87.9 2670.13
     108 2665.93  122.912660.521   128.1 2659.75  138.462660.523   140.1 2660.81
   148.2 2665.53   151.4 2666.06   164.2 2665.09   172.3 2665.64   176.3 2667.77
   180.3  2671.1   184.3 2673.24   195.7 2677.66   204.4 2681.88   212.4 2683.91
   236.5  2684.2   244.5 2683.36   256.6 2683.99   280.5 2683.58   298.7 2685.18
#Mann= 3 ,-1,0
       0      .1       0  122.91    .045       0  138.46      .1       0
Bank Sta=122.91,138.46
XS Rating Curve= 0 ,0
Exp/Cntr(USF)=0,0
Exp/Cntr=0.3,0.1

Type RM Length L Ch R = 1 ,2627    ,254.8,250.7,245.6
XS GIS Cut Line= 2
2197342.80985706607728.0667021812197725.75470791  607623.9860429
#Sta/Elev= 30
       0 2702.19     6.7 2697.29    13.8 2694.06    22.1 2691.65    34.6 2690.28
    38.7 2688.46      47  2683.3    67.7 2666.32    80.2 2658.35    88.5 2655.25
    96.8  2650.7   121.6 2649.19   134.1 2650.08  140.572647.819   143.6 2646.95
  152.662647.818   166.4 2650.27   175.5 2654.21   187.9 2655.66   208.7 2655.87
     217 2658.09   229.4 2663.67   233.5 2664.24   282.4  2665.2   308.2 2668.02
   328.9 2668.26   341.3 2675.16   366.2  2686.4   374.5 2687.95   396.8 2699.88
#Mann= 4 ,-1,0
       0      .1       0  140.57    .045       0  152.66      .1       0
     260     .08       0
Bank Sta=140.57,152.66
XS Rating Curve= 0 ,0
Exp/Cntr=0.3,0.1

Type RM Length L Ch R = 1 ,2376    ,149.1,148.6,146.6
XS GIS Cut Line= 2
2197478.63687715607980.0008746022197768.88347479607705.410732429
#Sta/Elev= 30
       0  2666.7     7.6 2665.43    21.6 2657.22    35.2 2651.79    40.7 2648.32
    51.7  2638.8    56.8 2635.24   72.112631.906    79.2 2631.24   89.712631.906
   112.2  2633.5   130.4 2638.29   145.3 2638.19   156.3  2641.9   167.3 2643.81
     202 2644.57   219.5 2642.03   231.1 2642.21   255.4 2648.47   260.2 2650.25
   271.8 2657.09   289.3 2661.81   297.4 2662.86     330 2663.28   347.5 2671.82
   356.8 2672.09   368.1 2673.92   376.6 2679.01   387.9 2682.68   399.6 2687.79
#Mann= 4 ,-1,0
       0      .1       0   72.11    .045       0   89.71      .1       0
     280     .08       0
Bank Sta=72.11,89.71
XS Rating Curve= 0 ,0
Exp/Cntr(USF)=0,0
Exp/Cntr=0.3,0.1

Type RM Length L Ch R = 1 ,2228    ,272.5,288.8,298.9
XS GIS Cut Line= 3
2197485.26850466608061.8746981832197603.79389431608053.182836275
2197812.74976645 607813.67375258
#Sta/Elev= 30
       0  2661.8    14.9 2655.75    33.3 2649.38      47 2646.67    66.9 2640.06
    75.1 2639.29   107.2  2632.9   134.8 2629.04   150.7 2628.54   171.9 2629.64
   187.9 2626.85   193.2 2626.43   203.8 2627.05  221.142625.328   228.9 2624.57
  236.682625.329   240.9 2627.37   246.2 2632.13   251.6 2633.43   278.1 2632.89
   286.4    2634   289.8 2635.15   299.3 2640.37   311.9 2643.19   323.2 2648.67
   340.2 2654.07   356.7 2661.08   379.9  2661.7   393.2 2669.78   436.7 2685.95
#Mann= 4 ,-1,0
       0      .1       0  221.14    .045       0  236.68      .1       0
  348.84     .08       0
Bank Sta=221.14,236.68
XS Rating Curve= 0 ,0
Exp/Cntr(USF)=0,0
Exp/Cntr=0.3,0.1

Type RM Length L Ch R = 1 ,1939    ,107,95.9,88.6
XS GIS Cut Line= 4
2197487.06727625608128.1952473852197686.06212171608134.064523237
2197799.13534344608259.2273347162197919.79386926 608217.75427951
#Sta/Elev= 30
       0 2656.74    21.1 2648.34    49.1 2639.63    65.1 2636.55    81.1 2635.27
    89.1 2633.96   113.2 2625.62   121.2 2623.94   145.2 2622.32   173.1 2622.33
   224.8 2618.91   273.8 2617.06   285.8 2615.21  296.012611.327   301.9 2610.83
  311.58 2611.32   321.7 2612.47   354.2 2610.87   368.9 2611.39   373.1 2613.37
   381.5 2621.15   395.4 2631.25   398.5  2633.2     408 2636.93   415.4 2640.64
   428.1 2644.72     445 2651.15   470.4 2658.02   474.6 2660.05   495.3 2661.24
#Mann= 3 ,-1,0
       0      .1       0  296.01    .045       0  311.58      .1       0
#XS Ineff= 2 , 0
                          337.89         2620.45
Permanent Ineff=
       F       F
Bank Sta=296.01,311.58
XS Rating Curve= 0 ,0
Exp/Cntr(USF)=0,0
Exp/Cntr=0.3,0.1

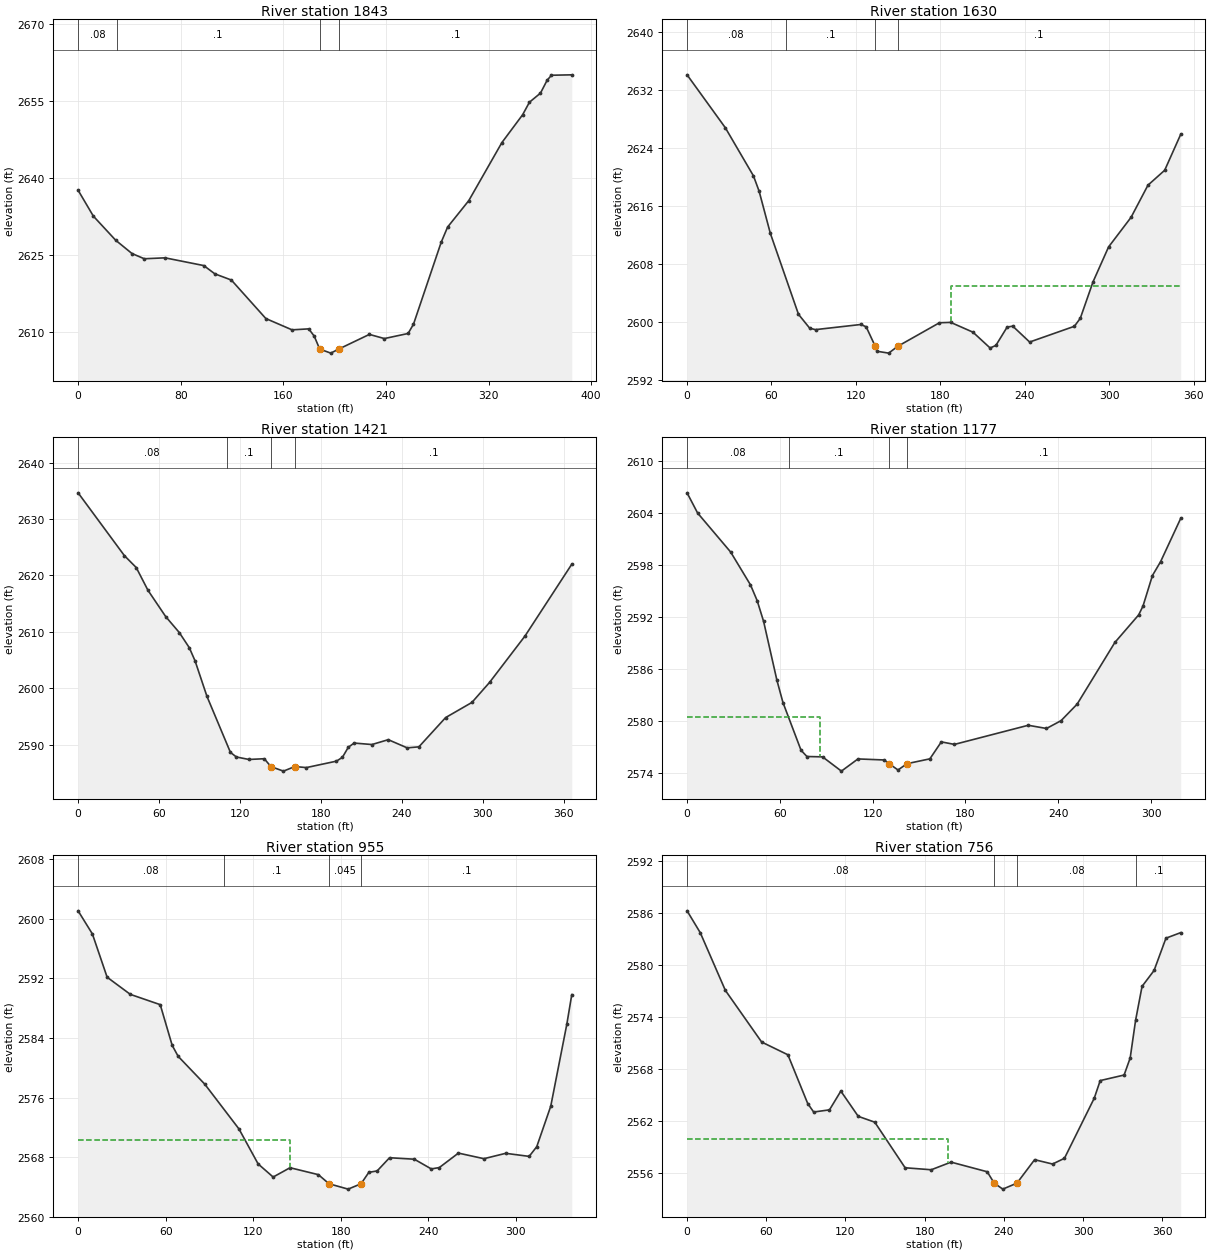
Type RM Length L Ch R = 1 ,1843    ,209.2,212.6,214.1
XS GIS Cut Line= 2
 2197565.1207285608376.2175889592197922.81051897608234.105146957
#Sta/Elev= 30
       0 2637.56    11.9 2632.51    29.3 2627.81      42 2625.22    51.6  2624.2
    67.8 2624.38      98 2622.87   106.6 2621.26   119.5 2620.05   146.4 2612.54
   166.8 2610.34   179.8 2610.53   184.1 2609.12  188.362606.592     197  2605.8
  203.262606.595   227.1 2609.45   238.8 2608.64   257.3 2609.63   261.5 2611.44
   283.1 2627.42   288.1 2630.38   304.6 2635.53   330.4 2646.84   346.6 2652.28
   351.9 2654.72   360.5 2656.49   365.7 2659.01   369.1 2659.98   384.9 2660.06
#Mann= 4 ,-1,0
       0     .08       0      30      .1       0  188.36    .045       0
  203.26      .1       0
Bank Sta=188.36,203.26
XS Rating Curve= 0 ,0
Exp/Cntr(USF)=0,0
Exp/Cntr=0.3,0.1

Type RM Length L Ch R = 1 ,1630    ,212.1,209.2,206.4
XS GIS Cut Line= 2
2197621.06401702608516.3377148332197971.44926042608496.700372214
#Sta/Elev= 30
       0 2634.12    27.2 2626.82    47.2 2620.18    51.2 2618.08    59.2 2612.25
    79.2 2601.09    87.2 2599.17    91.3 2598.98   123.5 2599.69   127.3 2599.37
  133.79 2596.67   135.3 2595.99   143.3 2595.74  149.67 2596.67   179.4 2599.93
   187.4 2599.98   203.2 2598.63   215.4 2596.45   219.5  2596.8   227.5 2599.33
   231.5 2599.46   243.5 2597.27   275.3 2599.44   279.5 2600.54   288.6 2605.59
   299.6 2610.38   315.6 2614.47   327.6  2618.9   339.5 2620.96   350.9 2625.92
#Mann= 4 ,-1,0
       0     .08       0      70      .1       0  133.79    .045       0
  149.67      .1       0
#XS Ineff= 2 , 0
                           187.4            2605
Permanent Ineff=
       F       F
Bank Sta=133.79,149.67
XS Rating Curve= 0 ,0
Exp/Cntr=0.3,0.1

Type RM Length L Ch R = 1 ,1421    ,246.8,244.5,243.3
XS GIS Cut Line= 2
2197692.70619092608764.4778096522198027.89404183608617.857512815
#Sta/Elev= 30
       0 2634.66    34.3 2623.52    43.1  2621.4    51.8 2617.36    64.9 2612.71
      75 2609.87    82.4 2607.19    86.7 2604.84    95.5 2598.55   112.9 2588.61
   117.3 2587.79   126.6 2587.35     138 2587.48  142.932586.077   152.2 2585.28
  160.64 2586.09   169.2 2585.91   191.5 2587.05   195.9 2587.73   200.3 2589.52
   204.6 2590.26   217.8    2590   229.9 2590.86   243.9 2589.41   252.6 2589.59
   272.4 2594.78   291.9 2597.47     305 2601.03   331.2 2609.24   365.9 2621.99
#Mann= 4 ,-1,0
       0     .08       0     110      .1       0  142.93    .045       0
  160.64      .1       0
Bank Sta=142.93,160.64
XS Rating Curve= 0 ,0
Exp/Cntr(USF)=0,0
Exp/Cntr=0.3,0.1

Type RM Length L Ch R = 1 ,1177    ,219.4,222.2,219.2
XS GIS Cut Line= 3
 2197821.8026796608986.634776299 2197883.2462416608963.593440549
2198074.61733574608797.183793471
#Sta/Elev= 30
       0 2606.33     6.8    2604    28.2 2599.48      41 2595.69    45.3 2593.88
    49.5 2591.46    58.1 2584.66      62 2582.09    73.7 2576.57    77.5 2575.85
    87.6 2575.81    99.8 2574.16   110.5 2575.57   127.5 2575.45   130.5 2575.04
   136.4 2574.29  142.162575.019     157 2575.58   164.4 2577.54   172.9 2577.25
   220.6 2579.46   232.4 2579.09   241.8 2579.99   252.2  2581.9   276.6 2589.03
     292 2592.22   294.8 2593.24   300.9 2596.77   306.2 2598.38   319.2 2603.38
#Mann= 4 ,-1,0
       0     .08       0   65.62      .1       0   130.5    .045       0
  142.16      .1       0
#XS Ineff= 2 , 0
           86.07 2580.45
Permanent Ineff=
       F       F
Bank Sta=130.5,142.16
XS Rating Curve= 0 ,0
Exp/Cntr(USF)=0,0
Exp/Cntr=0.3,0.1

Type RM Length L Ch R = 1 ,955     ,195.3,198.2,198.1
XS GIS Cut Line= 3
2197885.24190968609150.0018727252197998.49950424609124.540863095
2198170.83129436608984.033947824
#Sta/Elev= 30
       0 2601.04     9.8 2597.94    19.9 2592.14    35.8 2589.84    56.3 2588.46
    64.5    2583    68.6 2581.53    86.8 2577.81   110.3 2571.79   123.4 2567.11
   133.7 2565.35   145.3  2566.6   164.7 2565.67  172.012564.449   185.1 2563.73
  193.96 2564.45   199.3 2565.98     205 2566.17   213.5 2567.94   230.5 2567.74
   242.1 2566.44   247.6 2566.62   260.7 2568.56   278.2 2567.81   293.1 2568.53
   309.2 2568.12   314.4 2569.42     324 2574.85     335 2585.82   338.4  2589.8
#Mann= 4 ,-1,0
       0     .08       0     100      .1       0  172.01    .045       0
  193.96      .1       0
#XS Ineff= 2 , 0
          145.36 2570.33
Permanent Ineff=
       F       F
Bank Sta=172.01,193.96
XS Rating Curve= 0 ,0
Exp/Cntr(USF)=0,0
Exp/Cntr=0.3,0.1

Type RM Length L Ch R = 1 ,756     ,81.3,85.2,88.7
XS GIS Cut Line= 2
2197979.35228014609323.5682590682198310.05275005609148.950606815
#Sta/Elev= 30
       0 2586.25      10 2583.73      29 2577.09    56.5 2571.14    76.4 2569.67
    91.4 2564.06    95.9 2563.08   107.9 2563.33   116.5 2565.49   129.7 2562.58
   142.2 2561.91   165.2 2556.66     185 2556.43     200 2557.31   227.4  2556.2
  232.652554.894   239.2  2554.2  249.932554.892   263.3 2557.59   276.9 2557.09
   285.9 2557.75   308.5 2564.68     313  2566.7   331.1 2567.34   335.7  2569.3
   339.8 2573.64   344.7 2577.55   353.8 2579.38   362.8  2583.1     374 2583.74
#Mann= 4 ,-1,0
       0     .08       0  232.65    .045       0  249.93     .08       0
     340      .1       0
#XS Ineff= 2 , 0
           197.8    2560
Permanent Ineff=
       F       F
Bank Sta=232.65,249.93
XS Rating Curve= 0 ,0
Exp/Cntr(USF)=0,0
Exp/Cntr=0.3,0.1

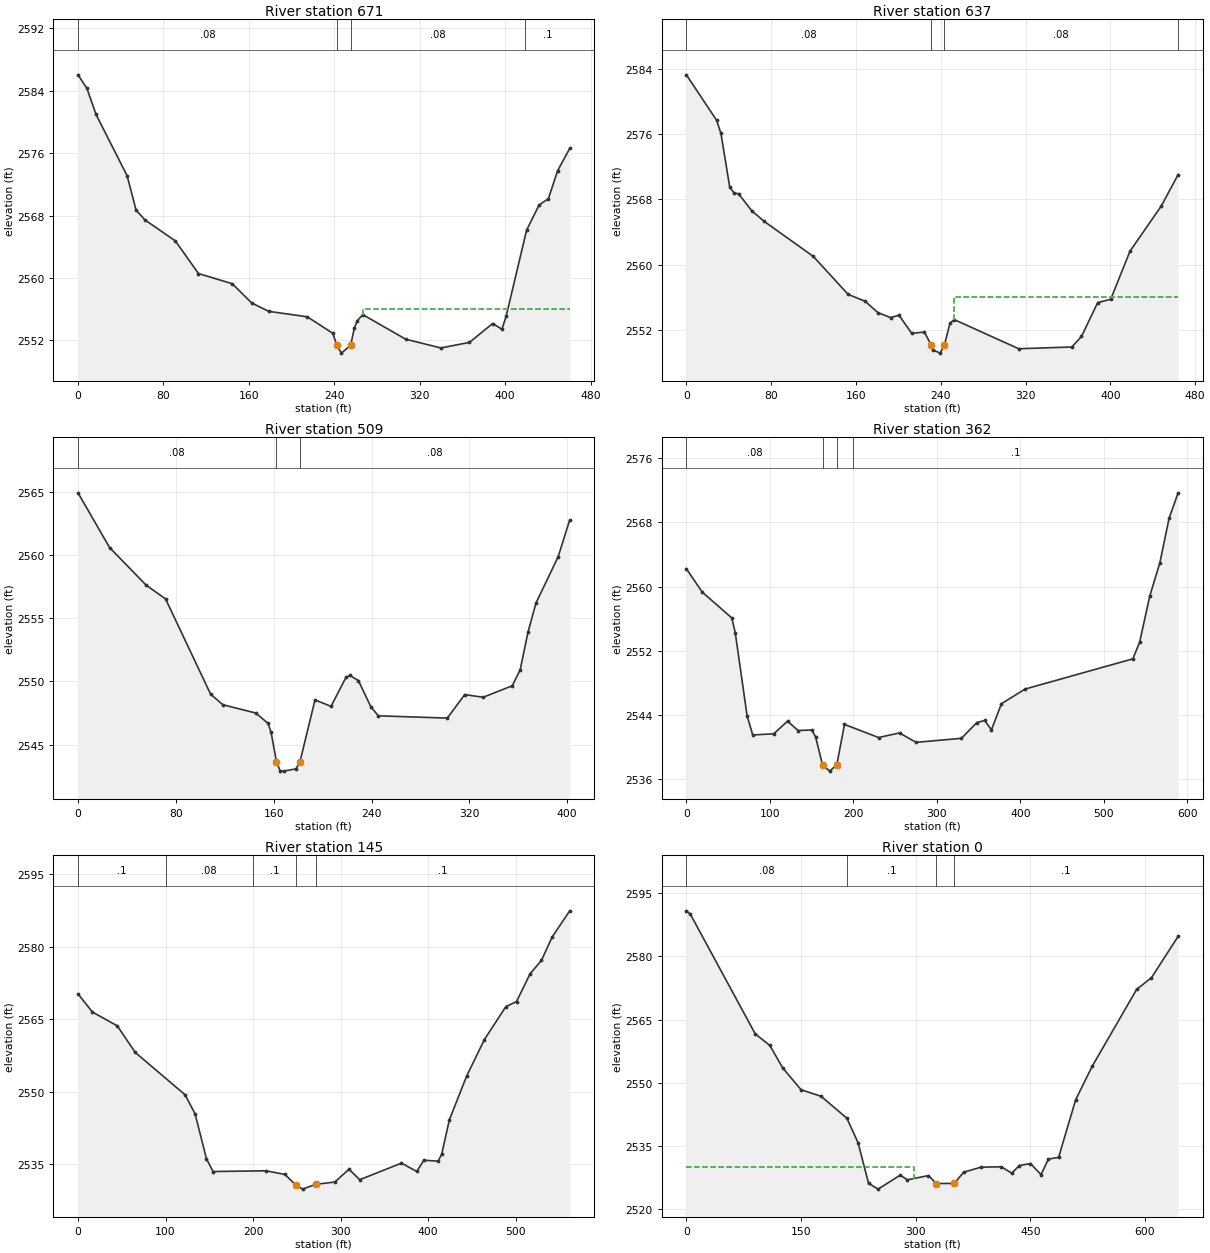
Type RM Length L Ch R = 1 ,671     ,34.1,34.4,34
XS GIS Cut Line= 4
2197980.08800739609330.5160615442198129.89830534609285.794149315
 2198292.0410384609292.9056726942198422.56822121609237.347993749
#Sta/Elev= 30
       0 2586.05     8.4  2584.3    16.8 2580.99      46  2573.1    54.4 2568.69
    62.7 2567.44    91.2 2564.74   112.8 2560.56   144.5 2559.25   162.6 2556.79
   178.6 2555.71   214.7 2555.01   238.7 2552.89   242.3 2551.35   246.7 2550.35
  255.33 2551.36   258.7 2553.51   261.5  2554.5   266.7 2555.29   306.8 2552.14
   339.9 2551.01   366.6 2551.73   388.3 2554.15     397 2553.41   400.9 2555.05
   420.1 2566.12   431.8 2569.35   440.5 2570.16   449.2 2573.76   460.5 2576.61
#Mann= 4 ,-1,0
       0     .08       0   242.3    .045       0  255.33     .08       0
  418.64      .1       0
#XS Ineff= 2 , 0
                           266.7            2556
Permanent Ineff=
       F       F
Bank Sta=242.3,255.33
XS Rating Curve= 0 ,0
Exp/Cntr(USF)=0,0
Exp/Cntr=0.3,0.1

Type RM Length L Ch R = 1 ,637     ,133.7,127.2,123.8
XS GIS Cut Line= 4
2197992.71725185609357.3057161882198129.35806206609319.607530753
2198291.50079512609326.7190541332198438.70932907609264.137648393
#Sta/Elev= 30
       0 2583.26    28.5 2577.69    32.6 2576.08    40.9 2569.49    45.1 2568.76
    49.2 2568.69    61.7 2566.59    73.5 2565.29   119.8    2561   152.6 2556.35
   168.6 2555.51   180.6 2554.12   192.6 2553.51   200.6 2553.79   212.6 2551.58
   224.6 2551.73     231 2550.13   232.6 2549.54   239.4 2549.15   243.4 2550.12
   248.7 2552.81   252.7 2553.26   313.5 2549.69   363.7  2549.9   372.8 2551.19
   388.1 2555.34   400.4 2555.75   418.6 2561.65   448.2  2567.2     464 2571.04
#Mann= 4 ,-1,0
       0     .08       0     231    .045       0   243.4     .08       0
     464      .1       0
#XS Ineff= 2 , 0
                           252.7            2556
Permanent Ineff=
       F       F
Bank Sta=231,243.4
XS Rating Curve= 0 ,0
Exp/Cntr(USF)=0,0
Exp/Cntr=0.3,0.1

Type RM Length L Ch R = 1 ,509     ,142.3,147,149.2
XS GIS Cut Line= 2
2198144.39980404609545.6139468852198459.65988499609296.023312751
#Sta/Elev= 30
       0 2564.94    25.8 2560.61    55.8 2557.62    71.6 2556.54   108.4    2549
   118.4 2548.16   145.4  2547.5   155.4 2546.68   157.9 2545.98  162.252543.651
   165.3 2542.91   168.1  2542.9   178.3 2543.08  181.522543.651   193.8 2548.54
   206.9 2548.03   219.1 2550.32   222.3 2550.48   229.3 2550.07   239.5 2547.99
   245.6 2547.28     302  2547.1   316.2 2548.96   331.3 2548.75   355.1 2549.66
   361.6 2550.93     368 2553.92   374.5 2556.21   392.6 2559.87   402.1  2562.8
#Mann= 3 ,-1,0
       0     .08       0  162.25    .045       0  181.52     .08       0
Bank Sta=162.25,181.52
XS Rating Curve= 0 ,0
Exp/Cntr=0.3,0.1

Type RM Length L Ch R = 1 ,362     ,212.2,217.9,216.8
XS GIS Cut Line= 3
2198184.31524032 609616.947563192198516.64157291609514.518214103
2198485.85857276609275.408008722
#Sta/Elev= 30
       0 2562.21    18.9 2559.32    54.3  2556.1    58.5 2554.26    72.7 2543.91
    79.4 2541.54   104.5 2541.68   121.1 2543.25   133.8 2542.09   150.1 2542.16
   154.7 2541.31  162.982537.813   171.5 2537.04  180.082537.815   189.3 2542.85
   230.1 2541.22   255.2 2541.79   274.9 2540.62   329.3 2541.12   347.8 2543.08
   357.2 2543.34   365.2 2542.17   377.3 2545.43   405.6 2547.25   534.6 2551.01
   542.7 2553.07   554.8  2558.8   566.9 2562.95     578  2568.5   588.8 2571.66
#Mann= 4 ,-1,0
       0     .08       0  162.98    .045       0  180.08     .08       0
     200      .1       0
Bank Sta=162.98,180.08
XS Rating Curve= 0 ,0
Exp/Cntr(USF)=0,0
Exp/Cntr=0.3,0.1

Type RM Length L Ch R = 1 ,145     ,147.7,144.5,140.1
XS GIS Cut Line= 2
2198184.03084997609801.6050267842198735.86358685609695.893248026
#Sta/Elev= 30
       0 2570.24    16.4  2566.5    44.9 2563.63    65.4 2558.14   122.3 2549.39
   133.8 2545.44   146.8 2536.14   154.3 2533.51   214.9 2533.66   236.4 2532.91
   248.6 2530.77   256.7 2529.87   271.7 2530.87   293.4 2531.33   309.7 2533.98
   321.9 2531.82   369.6 2535.24   387.1 2533.53   395.2 2535.84   411.5 2535.66
   415.6  2537.1   424.3 2544.16   444.1 2553.25   464.4  2560.8   488.9 2567.61
   501.1 2568.66   516.6  2574.4   529.6 2577.16   541.8 2582.01   561.9 2587.42
#Mann= 5 ,-1,0
       0      .1       0     100     .08       0     200      .1       0
   248.6    .045       0   271.7      .1       0
Bank Sta=248.6,271.7
XS Rating Curve= 0 ,0
Exp/Cntr=0.3,0.1

Type RM Length L Ch R = 1 ,0       ,397.1,397.1,397.1
XS GIS Cut Line= 4
2198258.06263147610113.3194466552198389.50388047609940.765138601
2198629.58581591609803.7296600362198768.47827125609746.596883544
#Sta/Elev= 30
       0 2590.79     5.2 2589.99    90.1 2561.59   109.1 2558.88   125.9 2553.57
     150 2548.35   176.2  2546.8     210 2541.59   224.6  2535.8   238.4 2526.16
   250.8 2524.77   279.9 2528.09   289.1 2526.98   316.7 2527.99   327.1  2526.1
   350.5 2526.12   362.8 2528.78   385.5 2529.98   412.1 2530.07   425.9 2528.55
   435.5 2530.36   450.3 2530.84   464.1  2528.2   473.7 2531.89   487.1 2532.32
   509.5 2546.01     531  2553.9   589.2 2572.15   608.6 2574.92   643.5 2584.74
#Mann= 4 ,-1,0
       0     .08       0     210      .1       0   327.1    .045       0
   350.5      .1       0
#XS Ineff= 2 , 0
        297.2142    2530
Permanent Ineff=
       F       F
Bank Sta=327.1,350.5
XS Rating Curve= 0 ,0
Exp/Cntr=0.3,0.1
LCMann Table=0

Chan Stop Cuts=-1
Use User Specified Reach Order=0
Composite Channel Slope=5